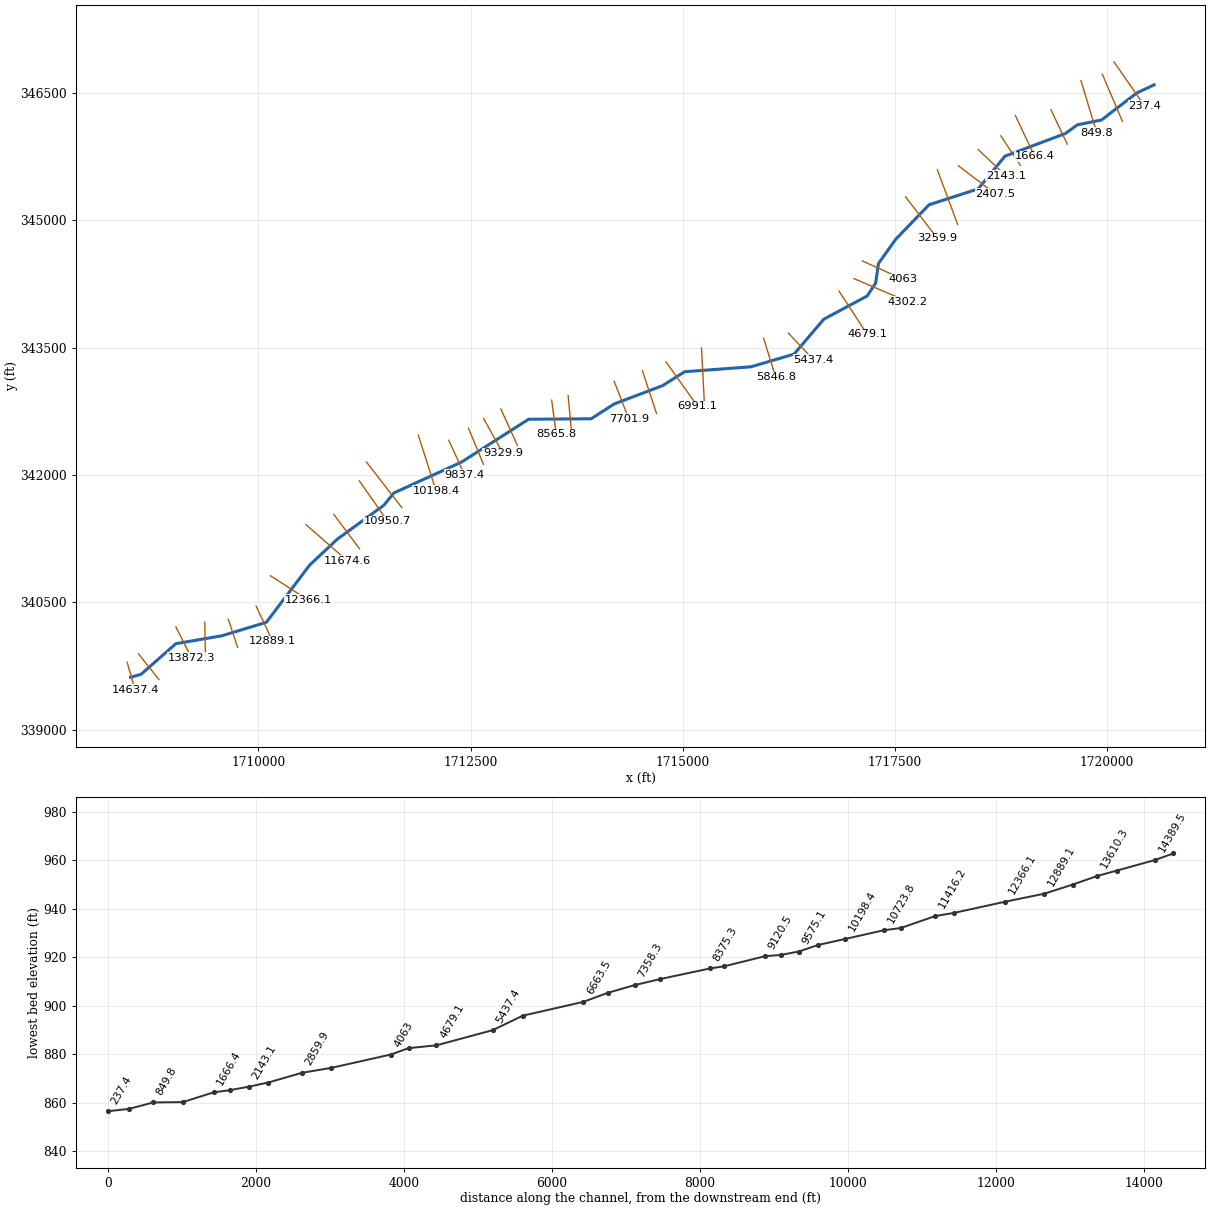
--- HEWETTCRK.prj (project) ---

Proj Title=HEWETTCRK
Current Plan=p01
Default Exp/Contr=0,0
English Units
Geom File=g01
Flow File=f01
Plan File=p01
BEGIN DESCRIPTION:
END DESCRIPTION:
DSS Export Rating Curves= 0
DSS Export Rating Curve Sorted= 0
DSS Export Volume Flow Curves= 0
DXF Filename=C:\HEWETTCRK.
DXF OffsetX= 0
DXF OffsetY= 0
DXF ScaleX= 0
DXF ScaleY= 0

--- HEWETTCRK.p01 (plan) ---

Plan Title=Floodplain
Program Version=4.00
Geom File=g01
Flow File=f01
K Sum by GR=0
Std Step Tol=0.01
Critical Tol=0.01
Num of Std Step Trials=20
Max Error Tol=0.3
Flow Tol Ratio=0.001
Split Flow NTrial=30
Split Flow Tol=0.02
Split Flow Ratio=0.02
Log Output Level=0
Friction Slope Method=1
Unsteady Friction Slope Method=2
Unsteady Bridges Friction Slope Method=1
Global Log Level=0
CheckData=False
Run HTab=0
Run UNet=0
Run PostProcess=0
UNET Theta=0
UNET Theta Warmup=0
UNET ZTol=0
UNET ZSATol=0
UNET MxIter=0
UNET MaxInSteps=0
UNET DtIC=0
UNET DtMin=0
UNET MaxCRTS=0
UNET WFStab=0
UNET SFStab=0
UNET WFX=0
UNET SFX=0
UNET DSS MLevel=0
UNET DZMax Abort=0
UNET Convert EG Bridges=0
UNET Use Existing IB Tables=0
UNET Froude Limit=0
UNET Froude Power=0
Write IC File=0
Echo Input=False
Echo Output=False
Write Detailed=0

--- HEWETTCRK.f01 (steady flow) ---

Flow Title=NFF Regression Equation
Program Version=4.00
Number of Profiles=1
Profile Names=P100yr
River Rch & RM=HEWETTCRK,Main      ,14637.4
1687.771
River Rch & RM=HEWETTCRK,Main      ,10950.7
1873.951
River Rch & RM=HEWETTCRK,Main      ,7358.3
2075.483
River Rch & RM=HEWETTCRK,Main      ,6991.1
2334.112
River Rch & RM=HEWETTCRK,Main      ,4063
2380.820
River Rch & RM=HEWETTCRK,Main      ,237.4
2643.550
Boundary for River Rch & Prof#=HEWETTCRK,Main      ,1
Up Type=0
Dn Type=3
Dn Slope=0.003979

--- HEWETTCRK.g01 (geometry) ---

Geom Title=USGS 10m DEM
Program Version=4.10

River Reach=HEWETTCRK       ,Main
Reach XY= 30
     1708493.152      339618.716     1708616.558      339652.328
      1709027.72      340013.688     1709568.601      340106.344
     1710093.267      340265.018     1710605.193       340940.25
      1710929.49      341243.699     1711479.636      341644.438
     1711594.298      341786.897     1712395.775      342152.889
     1713183.353      342655.549     1713921.128       342661.34
      1714190.99      342835.071     1714765.458      343052.813
     1715021.422      343214.961     1715802.051      343272.871
      1716311.66      343422.279     1716662.595      343833.442
     1717173.363      344106.778     1717272.969      344257.344
     1717306.556      344488.985     1717509.242      344773.903
     1717901.873      345180.432     1718482.132      345368.061
     1718797.164      345752.584     1719510.617      346020.129
     1719650.759      346122.051     1719934.519      346178.803
      1720352.63      346498.467     1720554.158      346592.282

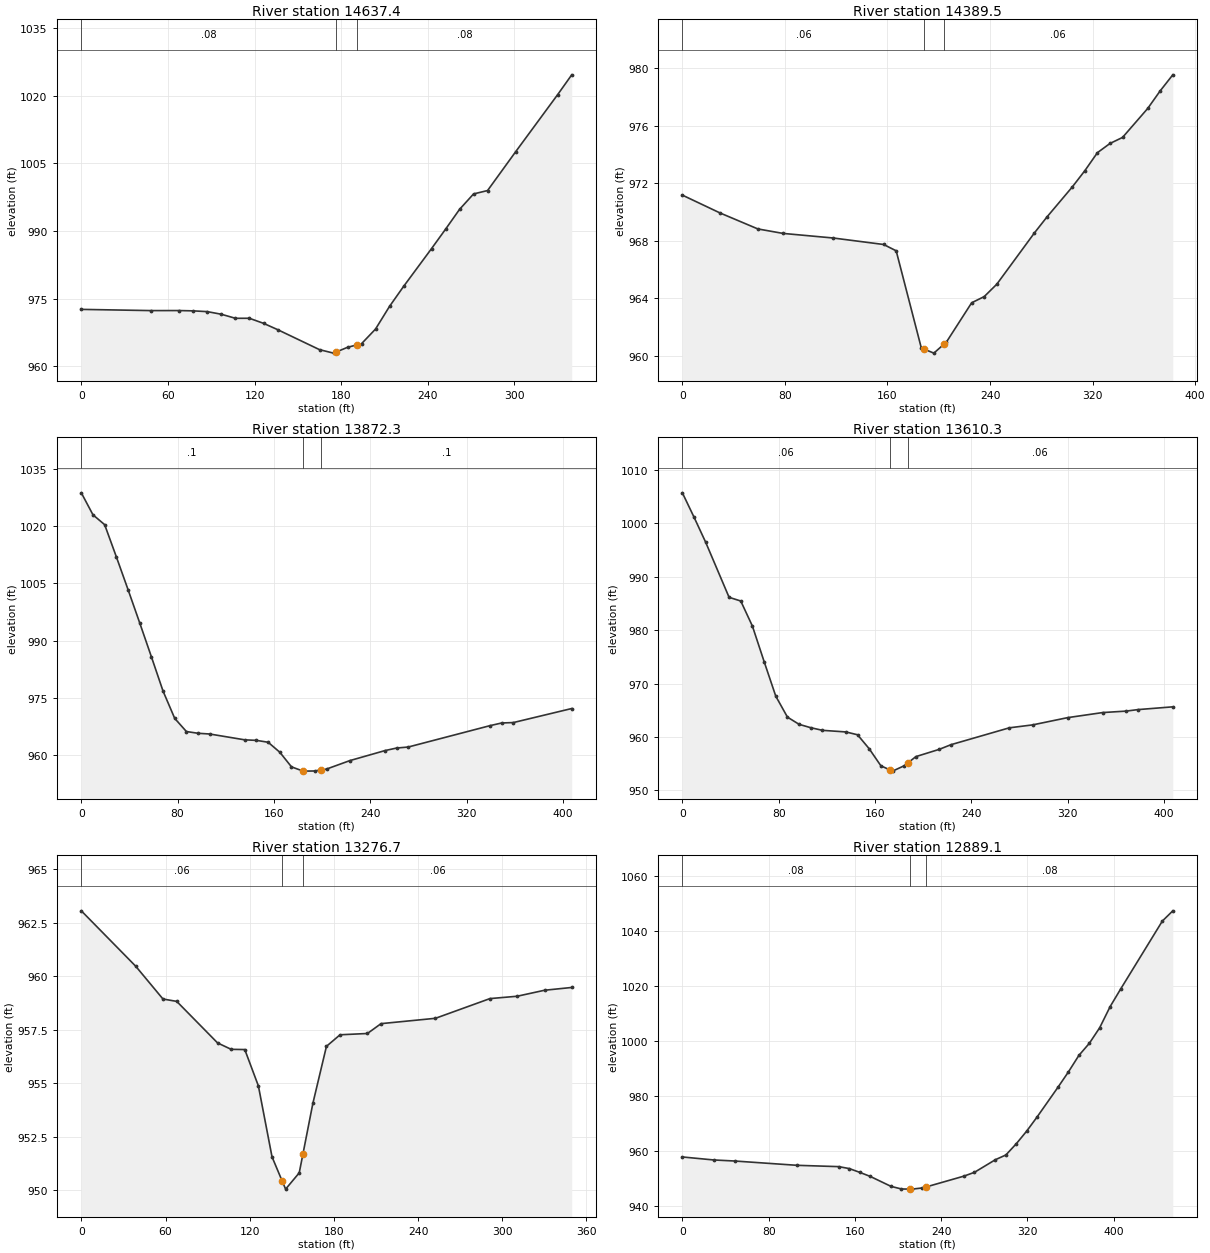
Type RM Length L Ch R = 1 ,14637.4 ,238.9,247.8,256.7
XS GIS Cut Line= 2
     1708452.998      339795.918     1708545.731      339469.165
#Sta/Elev= 27
       0   972.6    48.5  972.33    67.9  972.34    77.6  972.27    87.3   972.1
      97  971.52   106.8  970.62   116.4  970.63   126.2  969.51   135.9  968.12
     165  963.67   174.7   962.9   176.2   963.1   184.4  964.19   191.2  964.75
   194.1  964.99   203.8  968.24   213.5  973.27   223.2  977.68   242.6  986.08
   252.3  990.38     262  994.78   271.7   998.2   281.4  998.95   300.8 1007.53
     330 1020.24   339.7 1024.61
#Mann= 3 , 0 , 0
       0     .08       0   176.2    .045       0   191.2     .08       0
Bank Sta=176.2,191.2
XS Rating Curve= 0 ,0
Exp/Cntr=0.3,0.1

Type RM Length L Ch R = 1 ,14389.5 ,521.8,517.2,512.6
XS GIS Cut Line= 2
     1708588.095       339891.21     1708827.266      339592.534
#Sta/Elev= 25
       0  971.17    29.4  969.93    58.9  968.82    78.5  968.51   117.7  968.19
     157  967.74   166.8   967.3   186.4  960.55   188.8  960.46   196.2  960.19
   203.8  960.79     206  960.96   225.7  963.69   235.5  964.12   245.3  964.98
   274.7  968.55   284.5  969.66   304.2  971.74     314  972.87   323.8  974.12
   333.6  974.76   343.4  975.18     363  977.19   372.8  978.42   382.6  979.53
#Mann= 3 , 0 , 0
       0     .06       0   188.8    .045       0   203.8     .06       0
Bank Sta=188.8,203.8
XS Rating Curve= 0 ,0
Exp/Cntr=0.3,0.1

Type RM Length L Ch R = 1 ,13872.3 ,271.8,261.6,251.4
XS GIS Cut Line= 2
     1709027.735      340211.058     1709210.522      339846.929
#Sta/Elev= 30
       0 1028.75     9.7 1022.98    19.4  1020.4    29.1 1011.98    38.8  1003.4
    48.5  994.67    58.2  985.79    67.9  976.78    77.6  969.62    87.3  966.18
      97  965.72   106.7  965.53   135.8     964   145.5  963.86   155.2  963.37
   164.9  960.75   174.6  956.92     184  955.83   184.3   955.8     194  955.84
     199   956.1   203.7  956.34   223.1  958.56   252.2  961.18   261.9  961.85
   271.6  962.12   339.5  967.72   349.2  968.42   358.9  968.53   407.4  972.21
#Mann= 3 , 0 , 0
       0      .1       0     184    .045       0     199      .1       0
Bank Sta=184,199
XS Rating Curve= 0 ,0
Exp/Cntr=0.3,0.1

Type RM Length L Ch R = 1 ,13610.3 ,326.7,333.6,340.4
XS GIS Cut Line= 2
     1709367.706      340265.561     1709375.521      339858.204
#Sta/Elev= 30
       0 1005.74     9.7 1001.17    19.4  996.46    38.8  986.17    48.5  985.48
    58.2  980.77    67.9  974.14    77.6  967.65    87.3  963.73      97  962.38
   106.7  961.75   116.4  961.26   135.8  960.96   145.5  960.43   155.2  957.81
   164.9  954.62   172.1  953.88   174.6  953.62   184.3  954.63   187.1  955.12
     194  956.34   213.4   957.7   223.1  958.57   271.6  961.73     291  962.28
   320.1  963.64   349.2  964.59   368.6  964.86   378.3  965.14   407.4  965.66
#Mann= 3 , 0 , 0
       0     .06       0   172.1    .045       0   187.1     .06       0
Bank Sta=172.1,187.1
XS Rating Curve= 0 ,0
Exp/Cntr=0.3,0.1

Type RM Length L Ch R = 1 ,13276.7 ,384.8,387.5,390.2
XS GIS Cut Line= 2
     1709644.747      340301.377     1709754.637      339969.623
#Sta/Elev= 23
       0  963.05    38.8  960.46    58.2  958.93      68  958.82    97.1  956.88
   106.8  956.58   116.5  956.57   126.2  954.87   135.9  951.56     143  950.45
   145.6  950.05   155.3  950.81     158  951.71     165  954.05   174.7  956.72
   184.4  957.26   203.9  957.32   213.6  957.78   252.4  958.03   291.2  958.95
   310.6  959.06   330.1  959.34   349.5  959.47
#Mann= 3 , 0 , 0
       0     .06       0     143    .045       0     158     .06       0
Bank Sta=143,158
XS Rating Curve= 0 ,0
Exp/Cntr=0.3,0.1

Type RM Length L Ch R = 1 ,12889.1 ,510.2,522.9,535.7
XS GIS Cut Line= 2
      1709972.86      340455.225     1710166.048       340043.54
#Sta/Elev= 30
       0  957.96      29  956.87    48.4  956.49   106.4  954.92   145.1  954.44
   154.8  953.73   164.5  952.36   174.2  950.89   193.5  947.26   203.2  946.31
   210.9  946.27   212.9  946.26   222.5  946.69   225.9  947.04   261.2     951
   270.9  952.38   290.3  956.97     300  958.68   309.6  962.74   319.3  967.36
     329  972.53   348.3  983.31     358  988.89   367.7  994.89   377.4   999.3
     387 1004.96   396.7 1012.66   406.4 1019.02   445.1 1043.76   454.8 1047.49
#Mann= 3 , 0 , 0
       0     .08       0   210.9    .045       0   225.9     .08       0
Bank Sta=210.9,225.9
XS Rating Curve= 0 ,0
Exp/Cntr=0.3,0.1

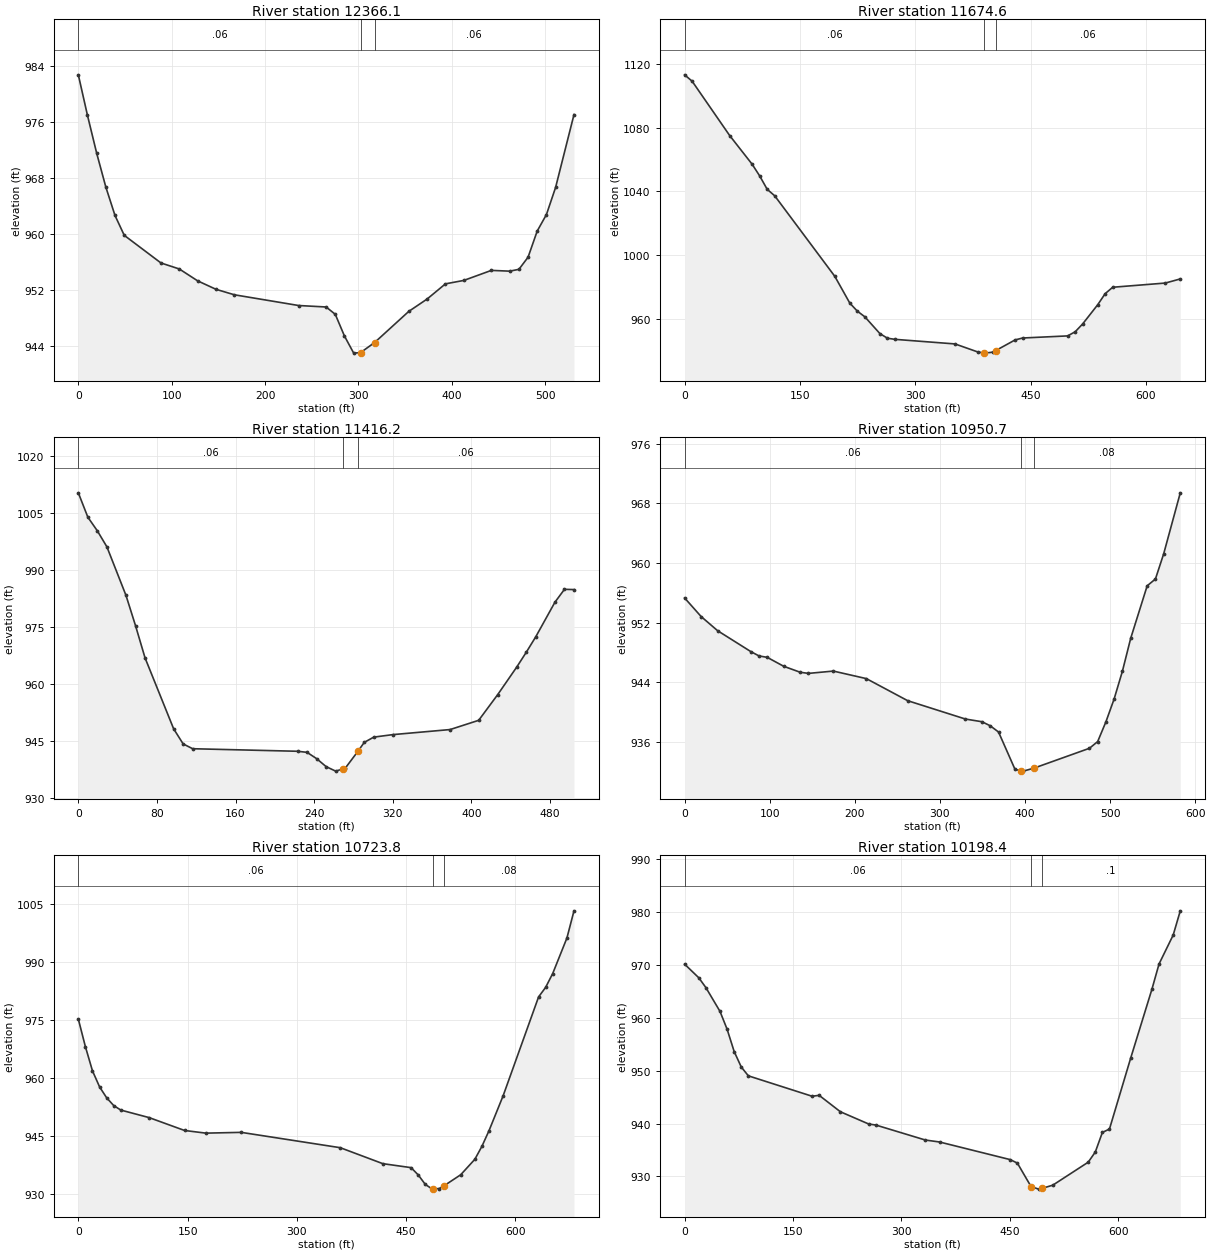
Type RM Length L Ch R = 1 ,12366.1 ,694.7,691.3,688
XS GIS Cut Line= 2
     1710140.663      340813.726     1710587.857      340527.492
#Sta/Elev= 30
       0  982.68     9.8   976.9    19.7  971.48    29.5  966.66    39.3  962.62
    49.2  959.79    88.5  955.85   108.2  954.99   127.8   953.3   147.5  952.09
   167.2  951.31     236  949.78   265.5  949.57   275.3  948.52   285.1  945.43
     295  942.99   302.4  943.07   317.4   944.5     354  948.94   373.6   950.7
   393.3  952.87     413  953.36   442.5  954.79   462.1  954.68     472  954.94
   481.8  956.67   491.6   960.4   501.5  962.76   511.3  966.62     531  977.01
#Mann= 3 , 0 , 0
       0     .06       0   302.4    .045       0   317.4     .06       0
Bank Sta=302.4,317.4
XS Rating Curve= 0 ,0
Exp/Cntr=0.3,0.1

Type RM Length L Ch R = 1 ,11674.6 ,263,258.2,253.5
XS GIS Cut Line= 2
     1710561.085      341414.268     1711046.764      340990.258
#Sta/Elev= 30
       0  1113.2     9.8 1109.18    58.6 1075.06    87.9 1056.99    97.7 1049.64
   107.4 1041.28   117.2  1037.2   195.4  986.58   214.9  969.76   224.7  964.73
   234.4  961.19     254  950.64   263.8  947.74   273.5  947.03   351.7  944.15
     381  939.16   389.8  938.44   390.7  938.37   400.5  938.96   404.8  940.01
   429.8  946.65   439.6  947.87   498.2  949.19     508  951.79   517.7  956.69
   537.3  968.76     547  975.73   556.8  979.75   625.2  982.39   644.7  984.97
#Mann= 3 , 0 , 0
       0     .06       0   389.8    .045       0   404.8     .06       0
Bank Sta=389.8,404.8
XS Rating Curve= 0 ,0
Exp/Cntr=0.3,0.1

Type RM Length L Ch R = 1 ,11416.2 ,466.2,465.4,464.6
XS GIS Cut Line= 2
     1710888.771      341534.797     1711191.168      341131.005
#Sta/Elev= 30
       0  1010.2     9.7 1003.79    19.4 1000.19    29.1  995.99    48.5  983.24
    58.2  975.29    67.9  966.81      97  948.16   106.7  944.18   116.4  942.92
   223.1  942.25   232.8  941.97   242.5  940.32   252.2  938.22   261.9  937.03
   269.7  937.63   271.6  937.78   284.7  942.28     291  944.58   300.7  945.97
   320.2  946.63   378.4  947.96   407.5  950.39   426.9  957.16   446.3  964.42
     456  968.31   465.7   972.4   485.1  981.44   494.8  984.83   504.5  984.76
#Mann= 3 , 0 , 0
       0     .06       0   269.7    .045       0   284.7     .06       0
Bank Sta=269.7,284.7
XS Rating Curve= 0 ,0
Exp/Cntr=0.3,0.1

Type RM Length L Ch R = 1 ,10950.7 ,225.9,226.9,227.8
XS GIS Cut Line= 2
     1711188.931       341930.13     1711523.479      341453.221
#Sta/Elev= 30
       0  955.31    19.4  952.82    38.8  950.92    77.7  948.13    87.4  947.54
    97.1  947.35   116.5  946.15   135.9  945.35   145.6   945.2   174.8  945.51
   213.6   944.5   262.2  941.54   330.1  939.08   349.5  938.72   359.2  938.18
     369  937.34   388.4  932.32   395.6  932.16   398.1   932.1   410.6   932.5
   475.8  935.16   485.5  936.06   495.2  938.71   504.9  941.79   514.6   945.5
   524.3  949.89   543.7  956.94   553.4  957.85   563.1  961.23   582.6   969.4
#Mann= 3 , 0 , 0
       0     .06       0   395.6    .045       0   410.6     .08       0
Bank Sta=395.6,410.6
XS Rating Curve= 0 ,0
Exp/Cntr=0.3,0.1

Type RM Length L Ch R = 1 ,10723.8 ,533,525.1,517.3
XS GIS Cut Line= 2
     1711272.648      342152.372     1711690.306      341615.235
#Sta/Elev= 30
       0  975.21     9.7  968.08    19.4  961.83    29.2  957.66    38.9  954.84
    48.6  952.83    58.3  951.67    97.2  949.72   145.8  946.39     175   945.7
   223.6   945.9   359.6  941.93     418   937.8   456.8  936.77   466.6  934.88
   476.3  932.43     486  931.21   486.5  931.22   495.7  931.37   501.5  932.01
   524.9  934.93   544.3  938.93     554  942.28   563.8  946.36   583.2   955.4
   631.8  980.95   641.5  983.43   651.2  987.01   670.7   996.2   680.4 1003.23
#Mann= 3 , 0 , 0
       0     .06       0   486.5    .045       0   501.5     .08       0
Bank Sta=486.5,501.5
XS Rating Curve= 0 ,0
Exp/Cntr=0.3,0.1

Type RM Length L Ch R = 1 ,10198.4 ,358.3,361,363.7
XS GIS Cut Line= 2
     1711883.978      342468.762     1712093.023      341815.501
#Sta/Elev= 30
       0  970.16    19.6  967.58    29.4  965.73      49  961.21    58.8  957.84
    68.6  953.61    78.4  950.69    88.2  949.02   176.4  945.16   186.2  945.33
   215.6  942.22   254.8   939.9   264.6  939.71   333.2  936.87   352.8   936.5
   450.7  933.16   460.5   932.5   479.4  928.06   489.9  927.58   494.4  927.71
   509.5  928.33   558.5  932.68   568.3   934.6   578.1  938.31   587.9  938.95
   617.3  952.39   646.7  965.43   656.5  970.19   676.1  975.67   685.9  980.25
#Mann= 3 , 0 , 0
       0     .06       0   479.4    .045       0   494.4      .1       0
Bank Sta=479.4,494.4
XS Rating Curve= 0 ,0
Exp/Cntr=0.3,0.1

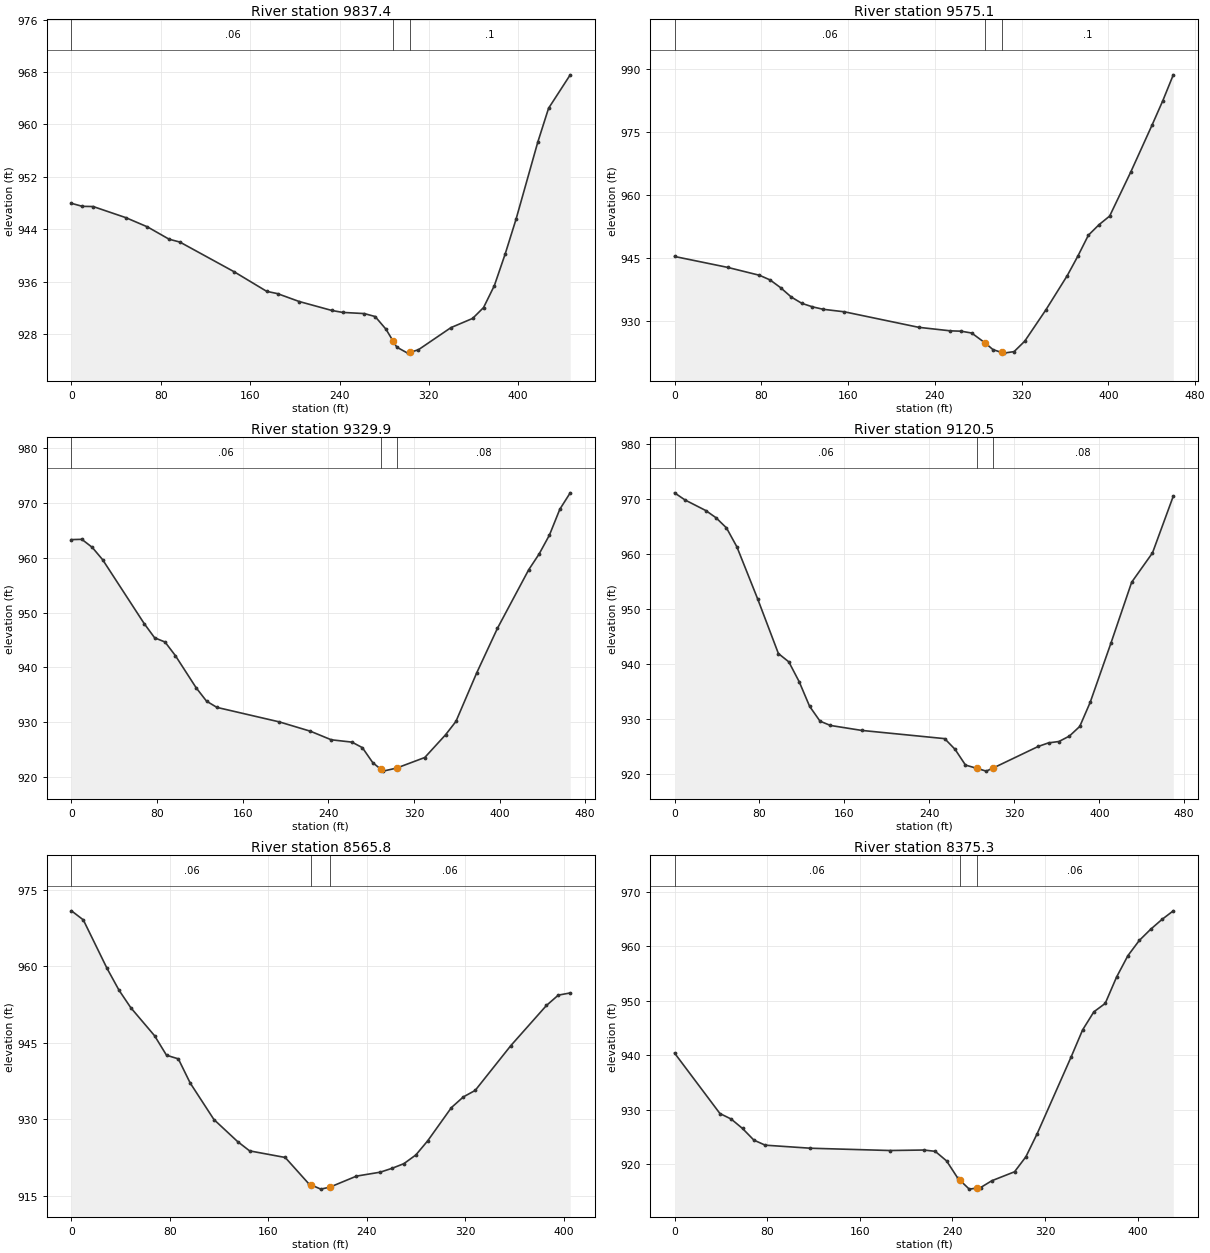
Type RM Length L Ch R = 1 ,9837.4  ,263.1,262.2,261.3
XS GIS Cut Line= 2
     1712243.002      342408.701     1712429.116      342002.692
#Sta/Elev= 30
       0  947.98     9.7  947.52    19.4  947.49    48.6   945.8      68  944.39
    87.4  942.51    97.1  942.07   145.6  937.55   174.8  934.56   184.5  934.21
   203.9  933.01     233  931.65   242.7  931.35   262.2  931.17   271.9  930.72
   281.6  928.79   288.1  926.95   291.3  926.05     301  925.14   303.1  925.25
   310.7  925.66   339.8  929.03   359.2  930.43     369  932.09   378.7  935.45
   388.4  940.28   398.1  945.57   417.5  957.28   427.2  962.47   446.6  967.57
#Mann= 3 , 0 , 0
       0     .06       0   288.1    .045       0   303.1      .1       0
Bank Sta=288.1,303.1
XS Rating Curve= 0 ,0
Exp/Cntr=0.3,0.1

Type RM Length L Ch R = 1 ,9575.1  ,242.6,245.2,247.8
XS GIS Cut Line= 2
     1712474.695      342551.096     1712651.282       342126.43
#Sta/Elev= 30
       0  945.42    48.9  942.83    78.3  940.95    88.1  939.84    97.8     938
   107.6  935.78   117.4  934.27   127.2  933.44     137  932.86   156.6  932.26
   225.1  928.57   254.4  927.73   264.2  927.65     274  927.21   286.7  924.79
   293.6  923.27   301.7  922.58   303.4  922.43   313.1  922.79   322.9  925.27
   342.5  932.76   362.1  940.86   371.8  945.46   381.6  950.48   391.4  952.98
   401.2  955.03   420.8  965.58   440.4  976.73   450.1   982.4   459.9  988.63
#Mann= 3 , 0 , 0
       0     .06       0   286.7    .045       0   301.7      .1       0
Bank Sta=286.7,301.7
XS Rating Curve= 0 ,0
Exp/Cntr=0.3,0.1

Type RM Length L Ch R = 1 ,9329.9  ,211.3,209.5,207.7
XS GIS Cut Line= 2
     1712654.996      342661.905     1712881.309      342254.546
#Sta/Elev= 30
       0  963.33     9.7  963.38    19.4  961.91    29.1  959.66      68  947.96
    77.7  945.38    87.4  944.61    97.1  942.12   116.5  936.24   126.2   933.8
   135.9  932.66   194.2  930.01   223.3   928.3   242.7  926.74   262.1  926.31
   271.8   925.3   281.5  922.56   288.8  921.39   291.2  921.01   303.8  921.57
   330.1   923.5   349.5  927.65   359.2  930.09   378.6  938.96     398  947.12
   427.2  957.82   436.9  960.69   446.6  964.17   456.3  968.89     466  971.88
#Mann= 3 , 0 , 0
       0     .06       0   288.8    .045       0   303.8     .08       0
Bank Sta=288.8,303.8
XS Rating Curve= 0 ,0
Exp/Cntr=0.3,0.1

Type RM Length L Ch R = 1 ,9120.5  ,561,554.4,547.8
XS GIS Cut Line= 2
      1712856.77      342776.718     1713051.403      342349.282
#Sta/Elev= 30
       0  971.14     9.8  969.85    29.4  967.92    39.1   966.6    48.9  964.76
    58.7  961.32    78.3  951.83    97.8   941.9   107.6  940.39   117.4  936.77
   127.2   932.3     137   929.6   146.8  928.82   176.1  927.92   254.4  926.42
   264.2  924.47     274  921.61   284.7  921.02   293.5  920.51   299.7  921.04
   342.5     925   352.2  925.65     362   925.9   371.8  926.88   381.6  928.64
   391.4  933.01     411  943.81   430.5  954.88   450.1  960.21   469.7  970.54
#Mann= 3 , 0 , 0
       0     .06       0   284.7    .045       0   299.7     .08       0
Bank Sta=284.7,299.7
XS Rating Curve= 0 ,0
Exp/Cntr=0.3,0.1

Type RM Length L Ch R = 1 ,8565.8  ,191.5,190.5,189.6
XS GIS Cut Line= 2
     1713455.662      342879.701     1713509.811      342478.275
#Sta/Elev= 30
       0  970.83     9.6  969.06    28.9  959.55    38.6  955.29    48.2  951.85
    67.5  946.37    77.2  942.55    86.8  941.84    96.4  937.12   115.7  929.96
     135  925.63   144.7  923.82   173.6  922.53   192.9  917.34   194.9  917.13
   202.5  916.33   209.9  916.72   231.5  918.88   250.8  919.65   260.4  920.41
     270  921.32   279.7  923.02   289.3  925.78   308.6   932.3   318.3  934.39
   327.9  935.66   356.8  944.42   385.8   952.3   395.4  954.32   405.1  954.75
#Mann= 3 , 0 , 0
       0     .06       0   194.9    .045       0   209.9     .06       0
Bank Sta=194.9,209.9
XS Rating Curve= 0 ,0
Exp/Cntr=0.3,0.1

Type RM Length L Ch R = 1 ,8375.3  ,666.9,673.3,679.7
XS GIS Cut Line= 2
     1713649.913      342935.347     1713689.004      342506.467
#Sta/Elev= 30
       0  940.39    39.2   929.3    48.9  928.29    58.7  926.56    68.5  924.43
    78.3   923.5   117.4  922.94     186  922.52   215.3  922.61   225.1  922.37
   234.9  920.62   244.7  917.42   246.4  917.08   254.5  915.44   261.4  915.64
   264.3  915.73     274  916.98   293.6  918.62   303.4  921.37   313.2  925.63
   342.6  939.74   352.4  944.64   362.1  947.95   371.9  949.49   381.7  954.32
   391.5  958.25   401.3  961.03   411.1  963.08   420.9  964.89   430.7  966.47
#Mann= 3 , 0 , 0
       0     .06       0   246.4    .045       0   261.4     .06       0
Bank Sta=246.4,261.4
XS Rating Curve= 0 ,0
Exp/Cntr=0.3,0.1

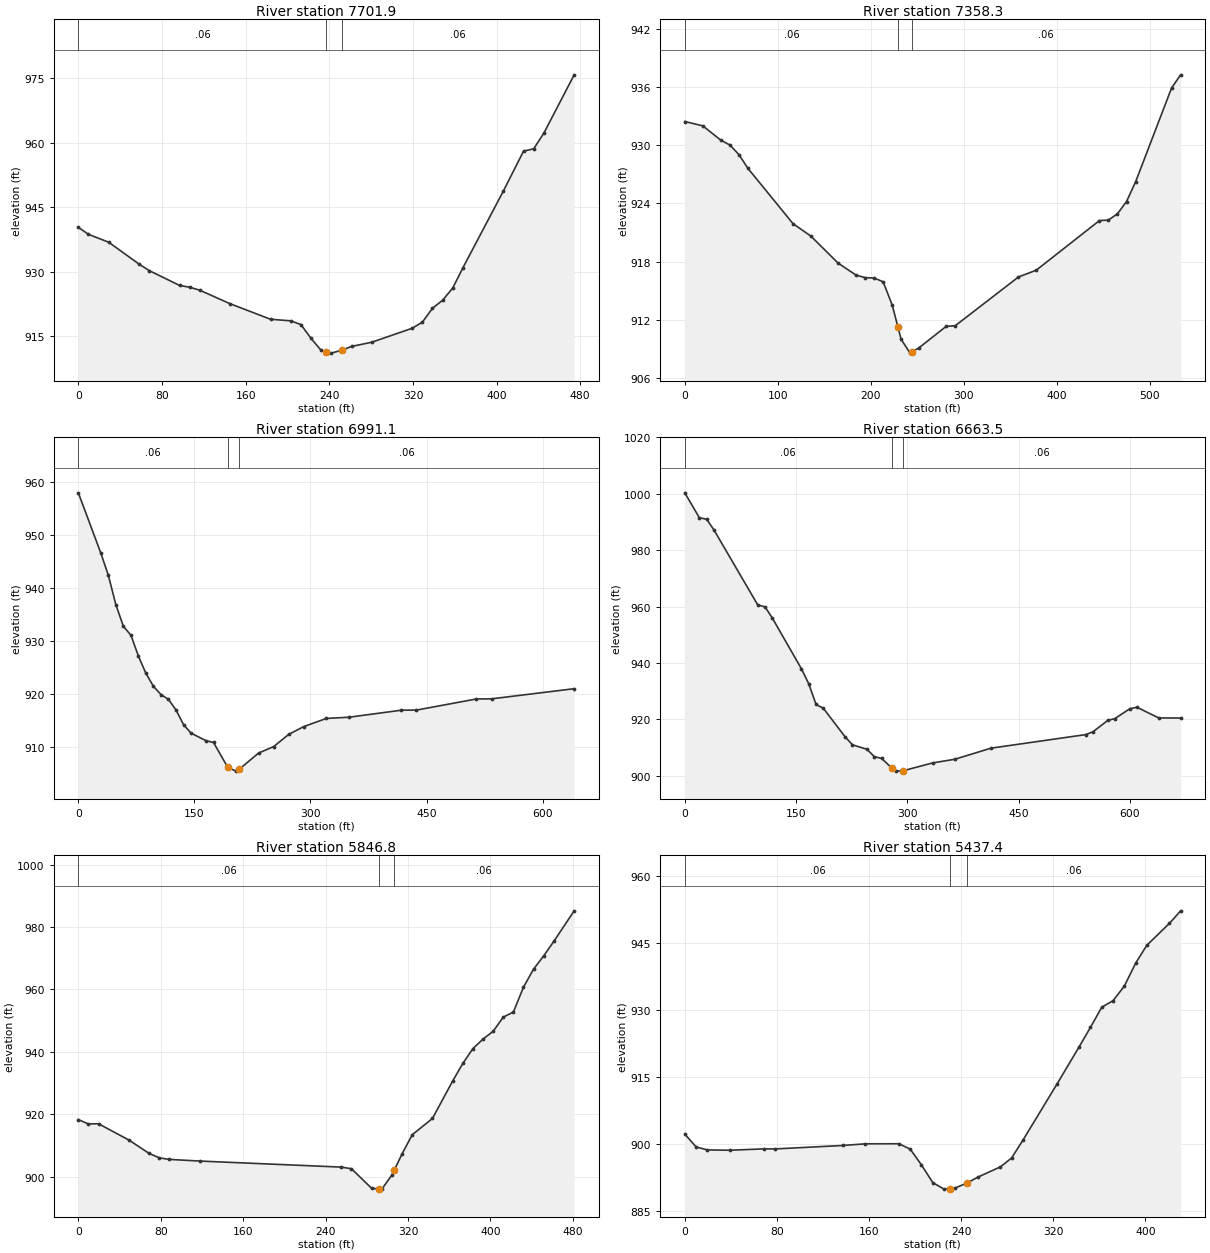
Type RM Length L Ch R = 1 ,7701.9  ,344.8,343.6,342.3
XS GIS Cut Line= 2
     1714191.341      343103.537     1714363.947      342661.858
#Sta/Elev= 30
       0  940.31     9.7  938.68      29  936.85    58.1  931.76    67.7  930.26
    96.8   926.8   106.4  926.39   116.1  925.69   145.2  922.54   183.9  918.93
   203.2  918.57   212.9  917.69   222.6  914.48   232.3  911.68   237.3  911.36
   241.9  911.06   252.3  911.77   261.3  912.62   280.6  913.59   319.4  916.85
     329  918.25   338.7  921.48   348.4  923.36   358.1  926.21   367.8   930.9
   406.5  948.75   425.8  958.03   435.5  958.57   445.2   962.2   474.2  975.77
#Mann= 3 , 0 , 0
       0     .06       0   237.3    .045       0   252.3     .06       0
Bank Sta=237.3,252.3
XS Rating Curve= 0 ,0
Exp/Cntr=0.3,0.1

Type RM Length L Ch R = 1 ,7358.3  ,360.2,367.1,373.9
XS GIS Cut Line= 2
     1714524.826      343228.115     1714691.604      342721.718
#Sta/Elev= 30
       0  932.45    19.4     932    38.8  930.52    48.5  930.03    58.2  929.04
    67.9  927.62   116.3  921.93   135.7  920.63   164.8  917.86   184.2  916.62
   193.9  916.36   203.6  916.32   213.3  915.93     223  913.55   229.3  911.23
   232.6  910.01   242.3  908.58   244.3   908.7     252  909.14   281.1  911.34
   290.8   911.4   358.7  916.42     378  917.13   445.9  922.24   455.6  922.29
   465.3  922.94     475   924.2   484.7  926.21   523.5  935.91   533.2  937.26
#Mann= 3 , 0 , 0
       0     .06       0   229.3    .045       0   244.3     .06       0
Bank Sta=229.3,244.3
XS Rating Curve= 0 ,0
Exp/Cntr=0.3,0.1

Type RM Length L Ch R = 1 ,6991.1  ,340.4,327.6,314.8
XS GIS Cut Line= 2
     1714802.776      343331.947     1715174.239      342809.892
#Sta/Elev= 30
       0  958.03    29.1  946.61    38.8  942.41    48.5  936.86    58.2  932.77
      68  931.07    77.7  927.11    87.4  923.84    97.1   921.4   106.8  919.85
   116.5  918.93   126.2  916.95   135.9  914.17   145.6  912.55     165  911.12
   174.7  910.78   193.1  906.07   203.9  905.36   208.1  905.74     233  908.79
   252.4     910   271.8  912.31   291.2  913.78   320.4  915.33   349.5  915.56
   417.4  916.89   436.9  916.91   514.5  919.02   533.9  919.04   640.7  920.96
#Mann= 3 , 0 , 0
       0     .06       0   193.1    .045       0   208.1     .06       0
Bank Sta=193.1,208.1
XS Rating Curve= 0 ,0
Exp/Cntr=0.3,0.1

Type RM Length L Ch R = 1 ,6663.5  ,811,816.5,822.1
XS GIS Cut Line= 2
     1715220.844      343494.362     1715255.963      342827.125
#Sta/Elev= 30
       0 1000.29    19.6  991.48    29.5   990.9    39.3  987.14    98.3  960.56
   108.1  959.88   117.9  955.93   157.2  937.91     167  932.62   176.9  925.27
   186.7  923.94   216.2  913.75     226  910.98   245.6  909.38   255.5  906.76
   265.3  906.17   278.9  902.75     285  901.65   293.9  901.76   334.1  904.57
   363.6  905.84   412.7  909.79   540.4   914.6   550.2  915.61   569.9  919.61
   579.7  920.28   599.4  923.71   609.2  924.31   638.7   920.5   668.2  920.47
#Mann= 3 , 0 , 0
       0     .06       0   278.9    .045       0   293.9     .06       0
Bank Sta=278.9,293.9
XS Rating Curve= 0 ,0
Exp/Cntr=0.3,0.1

Type RM Length L Ch R = 1 ,5846.8  ,399.1,409.3,419.5
XS GIS Cut Line= 2
     1715953.045      343610.516        1716095.      343150.578
#Sta/Elev= 30
       0  918.26     9.8  916.87    19.6  916.93    49.1  911.71    68.8  907.41
    78.6     906    88.4   905.5   117.9  904.97   255.4  903.03   265.2   902.5
   284.9  896.19   291.7  896.04   294.7  895.97   304.5  900.53   306.7  902.04
   314.4  907.33   324.2  913.41   343.8  918.63   363.5  930.68   373.3  936.26
   383.1  941.04   392.9  944.07   402.8   946.6   412.6  951.13   422.4  952.75
   432.2  960.73     442  966.52   451.9  970.81   461.7  975.43   481.4  985.21
#Mann= 3 , 0 , 0
       0     .06       0   291.7    .045       0   306.7     .06       0
Bank Sta=291.7,306.7
XS Rating Curve= 0 ,0
Exp/Cntr=0.3,0.1

Type RM Length L Ch R = 1 ,5437.4  ,762.1,758.2,754.3
XS GIS Cut Line= 2
     1716246.038       343669.32      1716540.23      343354.695
#Sta/Elev= 30
       0  902.28     9.8  899.41    19.6  898.74    39.2  898.67    68.5  898.97
    78.3  898.96     137  899.73   156.6   900.1     186  900.12   195.8  898.92
   205.6  895.38   215.4  891.43   225.2  889.97   230.4  890.11     235  890.24
   245.4  891.36   254.5  892.65   274.1  894.94   283.9  896.94   293.7  900.92
   323.1  913.38   342.6  921.82   352.4  926.16   362.2  930.66     372  932.12
   381.8  935.38   391.6   940.5   401.4  944.53     421  949.42   430.7  952.22
#Mann= 3 , 0 , 0
       0     .06       0   230.4    .045       0   245.4     .06       0
Bank Sta=230.4,245.4
XS Rating Curve= 0 ,0
Exp/Cntr=0.3,0.1

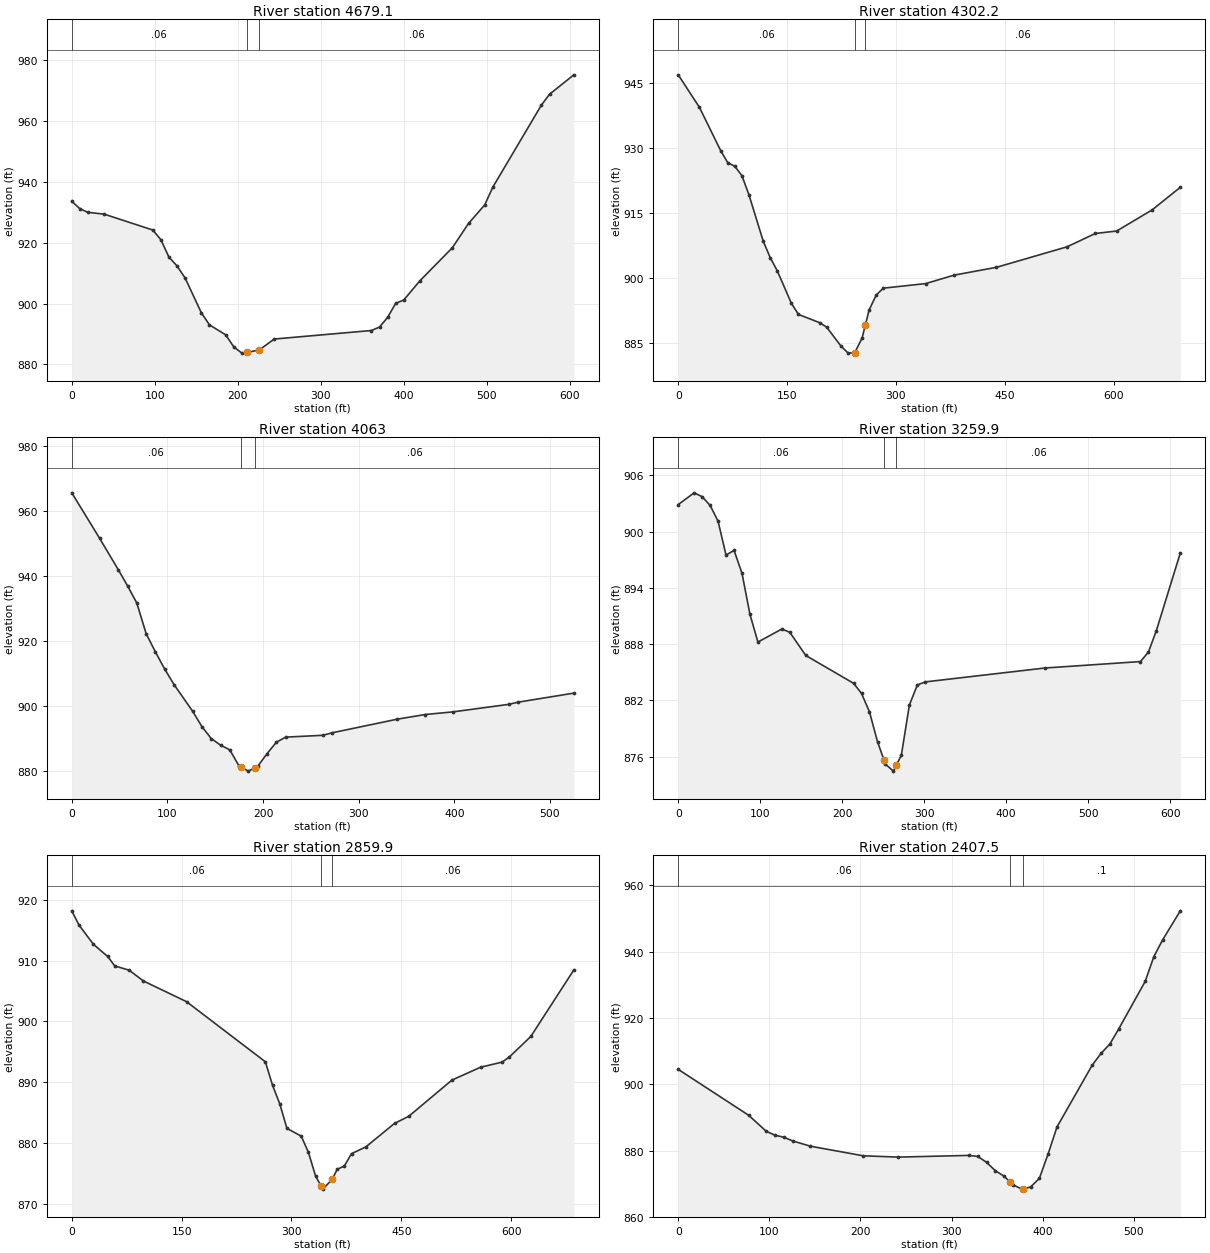
Type RM Length L Ch R = 1 ,4679.1  ,363.5,376.9,390.2
XS GIS Cut Line= 2
     1716841.463      344164.328      1717172.39      343658.331
#Sta/Elev= 30
       0  933.64     9.8  931.19    19.5     930      39  929.41    97.5   924.2
   107.3  921.01     117  915.29   126.8  912.37   136.5  908.42     156     897
   165.8  893.03   185.3  889.75     195  885.81   204.8  883.73   210.8  883.95
   225.8  884.78   243.8  888.36   360.8  891.16   370.6   892.3   380.3  895.47
   390.1   900.1   399.8  901.19   419.3  907.53   458.3  918.37   477.8  926.36
   497.3  932.46   507.1  938.32   565.6  965.28   575.4  968.84   604.6   975.2
#Mann= 3 , 0 , 0
       0     .06       0   210.8    .045       0   225.8     .06       0
Bank Sta=210.8,225.8
XS Rating Curve= 0 ,0
Exp/Cntr=0.3,0.1

Type RM Length L Ch R = 1 ,4302.2  ,239.6,239.1,238.8
XS GIS Cut Line= 2
     1717017.295      344311.553     1717653.646      344039.768
#Sta/Elev= 30
       0  946.91    29.2   939.4    58.5  929.38    68.2  926.61      78  925.75
    87.7  923.62    97.5  919.15     117  908.52   126.7  904.66   136.4  901.63
   155.9  894.09   165.7  891.51   194.9   889.6   204.7  888.54   224.2   884.2
   233.9  882.63     243  882.56   253.4  886.06     258  889.13   263.1  892.54
   272.9  895.99   282.6  897.58   341.1  898.64   380.1  900.59   438.6   902.4
     536  907.15     575  910.23   604.2  910.79     653  915.66     692   920.9
#Mann= 3 , 0 , 0
       0     .06       0     243    .045       0     258     .06       0
Bank Sta=243,258
XS Rating Curve= 0 ,0
Exp/Cntr=0.3,0.1

Type RM Length L Ch R = 1 ,4063    ,813.7,802.6,791.4
XS GIS Cut Line= 2
     1717116.136       344519.47     1717594.842      344303.992
#Sta/Elev= 30
       0  965.55    29.2  951.52    48.6  941.92    58.3  936.94      68  931.64
    77.8   922.2    87.5  916.59    97.2   911.3   106.9  906.58   126.4  898.34
   136.1  893.62   145.8  889.96   155.6  887.92   165.3  886.46     175  881.44
   176.6  881.19   184.7  879.93   191.6  880.97   194.4  881.39   204.2  885.31
   213.9   888.8   223.6  890.39   262.5  890.95   272.2  891.72   340.3  895.91
   369.4  897.34   398.6  898.16   456.9  900.47   466.6  901.14     525  903.93
#Mann= 3 , 0 , 0
       0     .06       0   176.6    .045       0   191.6     .06       0
Bank Sta=176.6,191.6
XS Rating Curve= 0 ,0
Exp/Cntr=0.3,0.1

Type RM Length L Ch R = 1 ,3259.9  ,406.9,400.2,393.5
XS GIS Cut Line= 2
     1717626.925      345272.898     1717999.317      344786.601
#Sta/Elev= 30
       0  902.88    19.4  904.13    29.2  903.72    38.9  902.79    48.6   901.1
    58.3  897.49    68.1  897.99    77.8  895.54    87.5  891.16    97.2  888.21
   126.4   889.6   136.1  889.25   155.6  886.78   213.9  883.81   223.6  882.73
   233.3  880.76   243.1  877.58   251.2  875.58   252.8  875.18   262.5  874.44
   266.2  875.09   272.2  876.15     282  881.49   291.7  883.64   301.4  883.96
   447.2  885.44   563.9  886.13   573.6  887.14   583.3  889.43   612.5  897.72
#Mann= 3 , 0 , 0
       0     .06       0   251.2    .045       0   266.2     .06       0
Bank Sta=251.2,266.2
XS Rating Curve= 0 ,0
Exp/Cntr=0.3,0.1

Type RM Length L Ch R = 1 ,2859.9  ,439.6,452.4,465.2
XS GIS Cut Line= 2
     1718000.593      345592.654     1718239.185      344949.927
#Sta/Elev= 30
       0  918.22     9.8  915.89    29.4  912.73      49   910.7    58.8  909.14
    78.4  908.44    97.9  906.66   156.7  903.26   264.4  893.35   274.2  889.47
     284  886.44   293.8  882.39   313.4   881.1   323.2  878.42     333  874.51
   340.6  872.86   342.8  872.38   355.6  873.99   362.4  875.64   372.2  876.19
     382  878.22   401.6  879.34   440.7   883.2   460.3  884.39   519.1  890.34
   558.3  892.46   587.6   893.3   597.4  894.13   626.8  897.52   685.6  908.49
#Mann= 3 , 0 , 0
       0     .06       0   340.6    .045       0   355.6     .06       0
Bank Sta=340.6,355.6
XS Rating Curve= 0 ,0
Exp/Cntr=0.3,0.1

Type RM Length L Ch R = 1 ,2407.5  ,266.7,264.3,261.8
XS GIS Cut Line= 2
     1718246.864      345640.812     1718685.844      345307.407
#Sta/Elev= 30
       0   904.5    77.4  890.64    96.7   885.8   106.4  884.63     116  884.03
   125.7  882.91   145.1  881.33   203.1  878.43   241.8  878.04   319.1  878.55
   328.8  878.25   338.5  876.46   348.2  873.92   357.8  872.27     364  870.62
   367.5  869.69   377.2  868.38     379   868.5   386.8  869.02   396.5  871.64
   406.2  879.09   415.8  887.12   454.5  905.78   464.2  909.32   473.9  912.16
   483.5  916.65   512.6  931.01   522.2  938.54   531.9  943.61   551.2  952.32
#Mann= 3 , 0 , 0
       0     .06       0     364    .045       0     379      .1       0
Bank Sta=364,379
XS Rating Curve= 0 ,0
Exp/Cntr=0.3,0.1

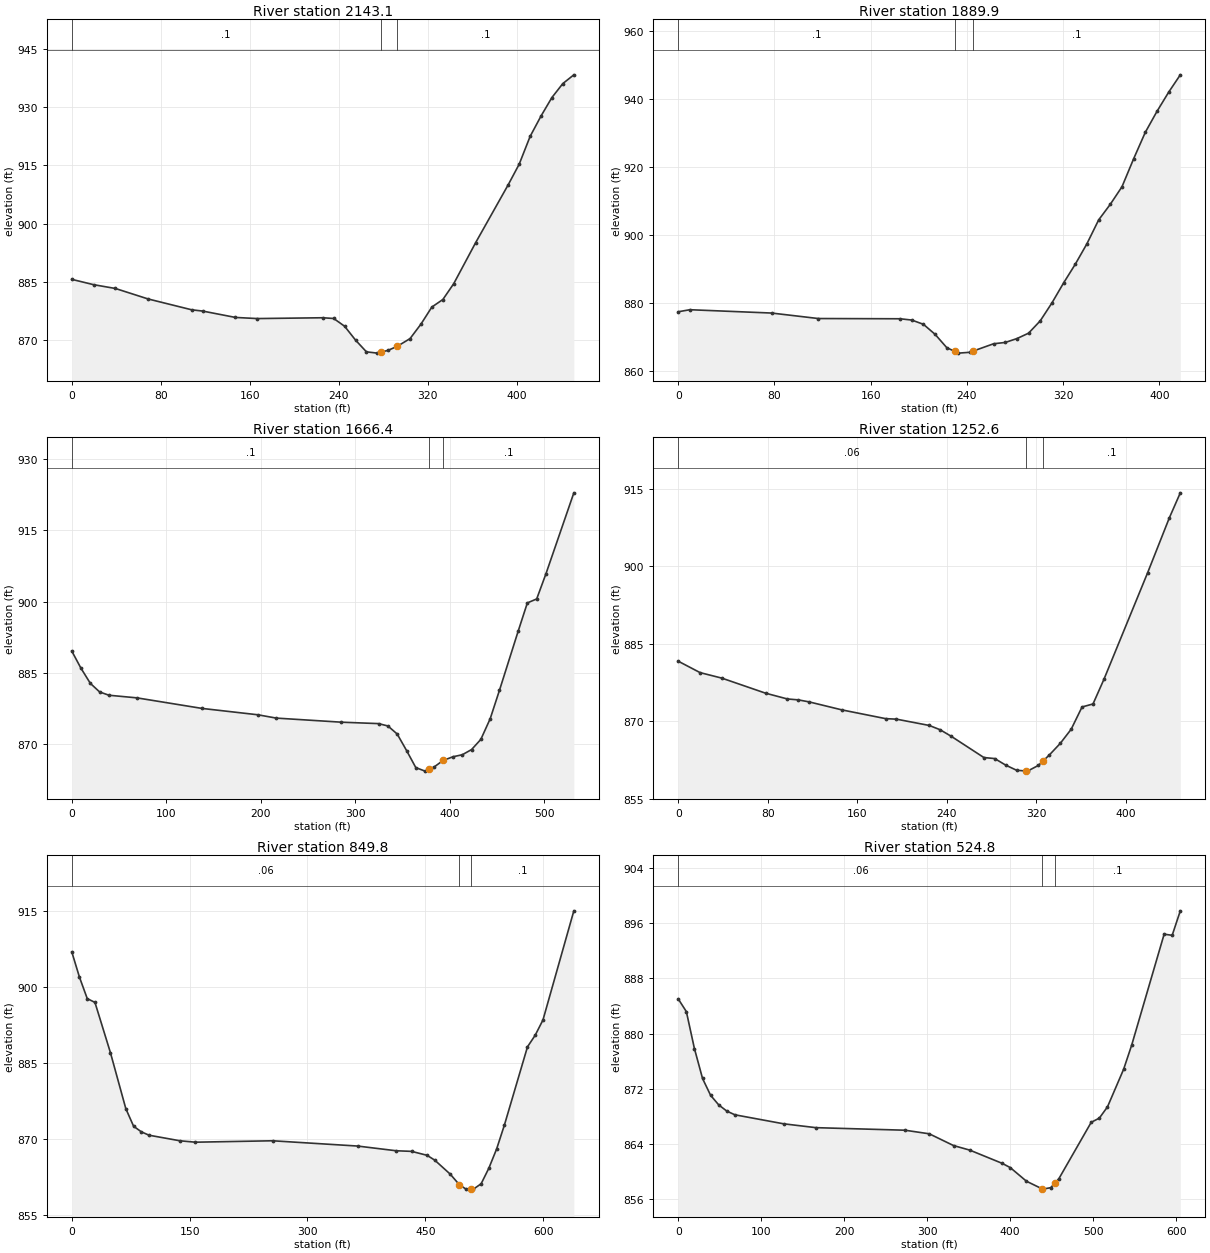
Type RM Length L Ch R = 1 ,2143.1  ,258.3,253.2,248.1
XS GIS Cut Line= 2
     1718481.418      345830.924       1718809.1      345520.832
#Sta/Elev= 30
       0  885.66    19.6  884.29    39.2  883.31    68.6  880.61   107.9  877.81
   117.7  877.49   147.1  875.85   166.7  875.56   225.6  875.77   235.4  875.58
   245.2  873.58     255  870.02   264.8  866.99   274.6  866.66   277.6  866.88
   284.4  867.39   292.6  868.43     304   870.4   313.8  874.13   323.6  878.53
   333.5  880.47   343.3  884.57   362.9  895.08   392.3  910.06   402.1  915.33
   411.9  922.47   421.7  927.72   431.5  932.49   441.3  936.08   451.2  938.33
#Mann= 3 , 0 , 0
       0      .1       0   277.6    .045       0   292.6      .1       0
Bank Sta=277.6,292.6
XS Rating Curve= 0 ,0
Exp/Cntr=0.3,0.1

Type RM Length L Ch R = 1 ,1889.9  ,226.8,223.5,220.2
XS GIS Cut Line= 2
     1718748.341      345992.313     1718978.868      345644.192
#Sta/Elev= 30
       0  877.39     9.7  877.99    77.7  877.01   116.5   875.4   184.5  875.33
   194.2  874.95   203.9   873.7   213.6  870.75   223.3  866.84   229.9  865.74
     233  865.23   242.8  865.48   244.9  865.79   262.2  867.98   271.9  868.37
   281.6   869.5   291.3  871.09     301  874.71   310.7  879.96   320.4  885.84
   330.1  891.33   339.8  897.35   349.6  904.39   359.3  908.99     369  914.14
   378.7  922.37   388.4  930.15   398.1   936.3   407.8  941.93   417.5  947.04
#Mann= 3 , 0 , 0
       0      .1       0   229.9    .045       0   244.9      .1       0
Bank Sta=229.9,244.9
XS Rating Curve= 0 ,0
Exp/Cntr=0.3,0.1

Type RM Length L Ch R = 1 ,1666.4  ,413.1,413.7,413.8
XS GIS Cut Line= 2
     1718919.172      346232.167     1719146.433      345752.007
#Sta/Elev= 30
       0  889.59     9.8  885.95    19.7  882.78    29.5  880.98    39.4  880.29
    68.9  879.74   137.7  877.52   196.8  876.18   216.4  875.48   285.3  874.62
   324.6  874.32   334.5  873.82   344.3  872.13   354.2  868.66     364  865.06
   373.8  864.32   377.8  864.69   383.7  865.24   392.8  866.56   403.3  867.34
   413.2  867.77     423  868.86   432.8     871   442.7  875.35   452.5  881.33
   472.2  893.71     482  899.72   491.9  900.56   501.7  905.86   531.2  922.89
#Mann= 3 , 0 , 0
       0      .1       0   377.8    .045       0   392.8      .1       0
Bank Sta=377.8,392.8
XS Rating Curve= 0 ,0
Exp/Cntr=0.3,0.1

Type RM Length L Ch R = 1 ,1252.6  ,406.8,402.8,399.4
XS GIS Cut Line= 2
     1719339.281      346299.548     1719531.195       345894.07
#Sta/Elev= 30
       0  881.58    19.5  879.37      39   878.3      78  875.39    97.5  874.27
   107.3  874.09     117   873.7   146.3  872.15   185.3  870.46     195  870.36
   224.3  869.14     234  868.31   243.8  867.06   273.1  862.93   282.8  862.73
   292.6  861.46   302.3  860.47   310.5  860.33   312.1   860.3   321.8  861.41
   325.5  862.17   331.6  863.43   341.3  865.66   351.1  868.41   360.8  872.72
   370.6   873.3   380.3  878.04   419.4   898.7   438.8  909.33   448.6  914.17
#Mann= 3 , 0 , 0
       0     .06       0   310.5    .045       0   325.5      .1       0
Bank Sta=310.5,325.5
XS Rating Curve= 0 ,0
Exp/Cntr=0.3,0.1

Type RM Length L Ch R = 1 ,849.8   ,322.5,324.9,327.4
XS GIS Cut Line= 2
     1719693.195      346640.781     1719878.708      346029.226
#Sta/Elev= 30
       0  906.96     9.8  901.96    19.7  897.73    29.5  896.98    49.2  887.07
    68.8  876.02    78.7  872.55    88.5  871.45    98.3  870.78   137.6  869.68
   157.3   869.4   255.6  869.68   363.8  868.64   412.9  867.71   432.6  867.59
   452.3  866.81   462.1  865.85   481.8  863.09   493.2  861.04   501.4  860.18
   508.2  860.15   511.3  860.14   521.1   861.2   530.9  864.27   540.8  868.06
   550.6  872.73   580.1  888.22   589.9   890.5   599.8  893.52   639.1  915.05
#Mann= 3 , 0 , 0
       0     .06       0   493.2    .045       0   508.2      .1       0
Bank Sta=493.2,508.2
XS Rating Curve= 0 ,0
Exp/Cntr=0.3,0.1

Type RM Length L Ch R = 1 ,524.8   ,282.7,287.4,292
XS GIS Cut Line= 2
      1719944.12      346718.726     1720181.507      346162.136
#Sta/Elev= 30
       0  885.01     9.8  883.17    19.5  877.83    29.3   873.5      39  871.07
    48.8  869.68    58.6  868.78    68.3  868.25   126.9  866.95   165.9  866.39
   273.3  866.02   302.6   865.5   331.8   863.8   351.4  863.14   390.4  861.23
   400.2  860.61   419.7  858.64   438.9  857.52   439.2   857.5   448.9  857.71
   453.9  858.37   458.7     859   497.7  867.16   507.5  867.77   517.3  869.39
   536.8  874.84   546.5  878.33   585.6  894.37   595.3  894.21   605.1  897.75
#Mann= 3 , 0 , 0
       0     .06       0   438.9    .045       0   453.9      .1       0
Bank Sta=438.9,453.9
XS Rating Curve= 0 ,0
Exp/Cntr=0.3,0.1

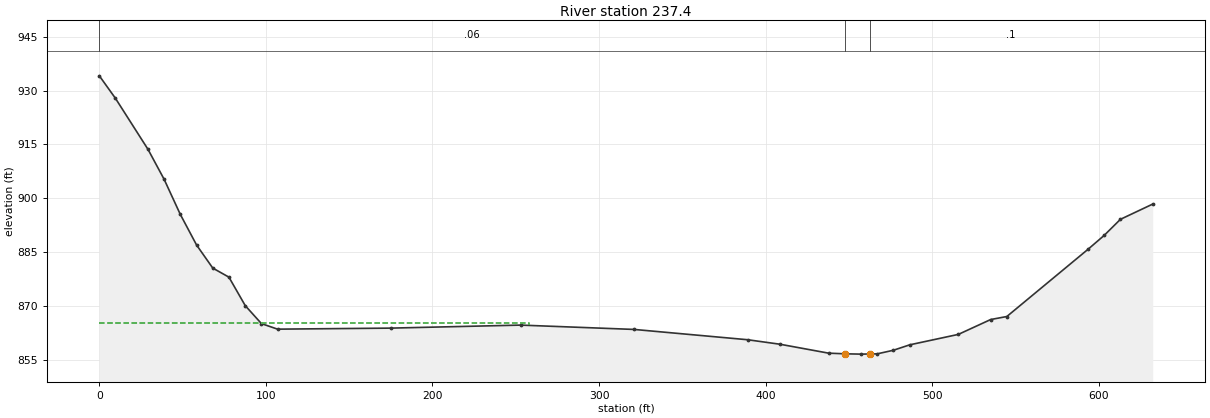
Type RM Length L Ch R = 1 ,237.4   ,243.3,237.3,231.4
XS GIS Cut Line= 2
     1720081.263      346863.919     1720441.793      346344.336
#Sta/Elev= 30
       0  934.09     9.7   927.8    29.2  913.61    38.9  905.25    48.6  895.48
    58.4  886.92    68.1  880.51    77.8  877.98    87.6  870.04    97.3  865.04
     107  863.49   175.1  863.78     253  864.62   321.1  863.41   389.2  860.54
   408.6  859.29   437.8   856.8   447.5  856.62   457.3  856.53   462.5  856.57
     467  856.61   476.7  857.61   486.5  859.12   515.7  862.03   535.1  866.17
   544.8  867.01   593.5  885.73   603.2   889.6     613   894.1   632.4  898.35
#Mann= 3 , 0 , 0
       0     .06       0   447.5    .045       0   462.5      .1       0
#XS Ineff= 2 , 0
          258.15  865.13
Permanent Ineff=
       F       F
Bank Sta=447.5,462.5
XS Rating Curve= 0 ,0
Exp/Cntr=0.3,0.1

Chan Stop Cuts=-1
Use User Specified Reach Order=0
Composite Channel Slope=5